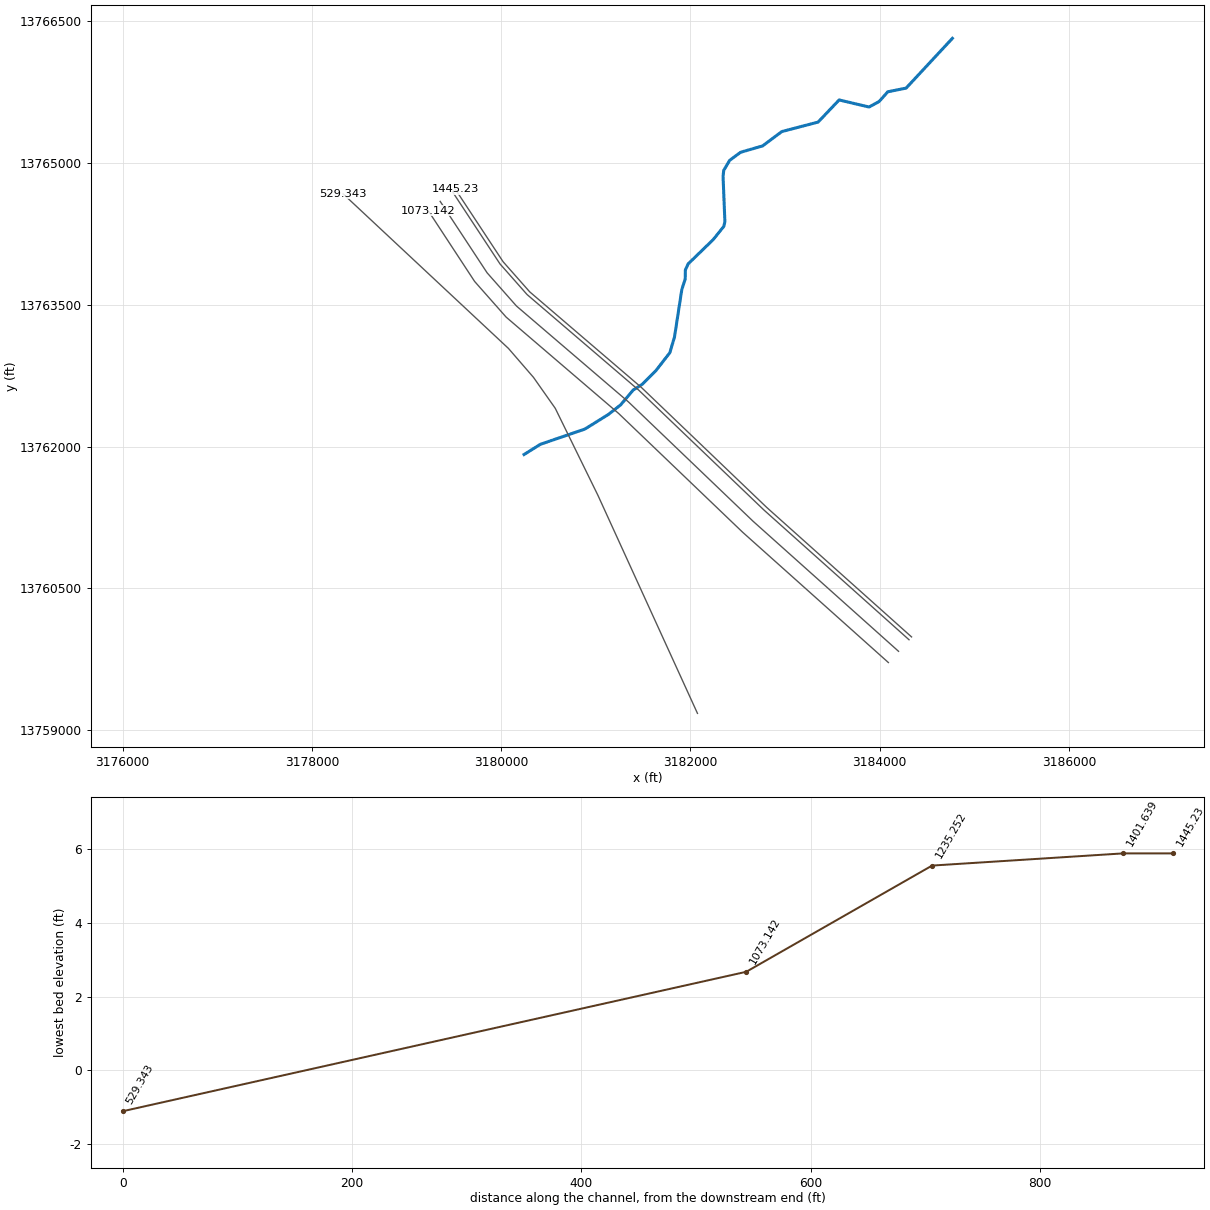
--- A118_00_00.prj (project) ---

Proj Title=A118-00-00
Current Plan=p01
Default Exp/Contr=.3,.1
English Units
Geom File=g01
Flow File=f01
Flow File=f02
Plan File=p01
Plan File=p02
Y Axis Title=Elevation
X Axis Title(PF)=Main Channel Distance
X Axis Title(XS)=Station
BEGIN DESCRIPTION:
Clear Creek Basin
Cedar Gully
A118-00-00
Flood Hazard Model
10, 2, 1 & 0.2% Events
Filename: A118_00_00.prj
Prepared by: Perry Vaught	Date: 4-30-04
Reviewed by: __________	Date:
Status: (FINAL)
END DESCRIPTION:
DSS Export Rating Curves= 0
DSS Export Rating Curve Sorted= 0
DSS Export Volume Flow Curves= 0
DXF OffsetX= 0
DXF OffsetY= 0
DXF ScaleX= 1
DXF ScaleY= 10

--- A118_00_00.p01 (plan) ---

Plan Title=FEMA Effective June 2007
Version=Version 3.0.1  Mar 2001
Short Identifier=FEMAeff0607
Geom File=g01
Flow File=f01
Subcritical Flow
K Sum by GR= 0
Std Step Tol= 0.003
Critical Tol= 0.003
Num of Std Step Trials= 20
Max Error Tol= 0.1
Flow Tol Ratio= 0.001
Split Flow NTrial= 30
Split Flow Tol= 0.02
Split Flow Ratio= 0.02
Log Output Level= 0
Friction Slope Method= 0
Unsteady Friction Slope Method= 2
Secant Critical Depth
Global Vel Dist= 0 , 0 , 0
Global Log Level= 0
CheckData=True
Encroach Param=-1 ,0,0, 0
Computation Interval=1HOUR
Output Interval=1HOUR
Run HTab= 0
Run UNet= 0
Run PostProcess= 0
UNET Theta= 1
UNET ZTol= 0.02
UNET ZSATol= 0.1
UNET MxIter= 20
UNET MaxInSteps= 20
UNET DtIC= 0
UNET DtMin= 0
UNET MaxCRTS= 20
UNET WFStab= 2
UNET SFStab= 1
UNET WFX= 1
UNET SFX= 1
UNET Convert EG Bridges=-1
UNET Use Existing IB Tables=-1
Instantaneous Interval=1HOUR
Write IC File= 0
Write Velocity= 0
Write Detailed= 0

--- A118_00_00.p02 (plan) ---

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Plan Title=Floodway
Short Identifier=Floodway0607
Geom File=g01
Flow File=f02
Encroach Param=-1 ,0,0, 2
Encroach River=A118-00-00
Encroach Reach=A118-00-00_0005
Encroach Node=1445.23
       1    4920    5063
Encroach Node=1401.639
       1 4903.66 5051.41
Encroach Node=1318
       1 4878.78    5061
Encroach Node=1235.252
       1 4878.78    5061
Encroach Node=1073.142
       1 4924.74 5092.37
Encroach Node=529.343
       1    4949    5058
IC Time=0

--- A118_00_00.f01 (steady flow) ---

Flow Title=FEMA Effective June 2007
Version=Version 3.0.1  Mar 2001
Number of Profiles= 4
Profile Names=10PCT_10yr, 2PCT_50yr, 1PCT_100yr, 0.2PCT_500yr
River Rch & RM=A118-00-00,A118-00-00_0005      ,1445.23
     848    1205    1393    1906
River Rch & RM=A118-00-00,A118-00-00_0005      ,1073.142
     893    1269    1467    2007
Boundary for River Rch & Prof#=A118-00-00,A118-00-00_0005      , 1
Up Type= 0
Dn Type= 3
Dn Slope=.007
Boundary for River Rch & Prof#=A118-00-00,A118-00-00_0005      , 2
Up Type= 0
Dn Type= 3
Dn Slope=.007
Boundary for River Rch & Prof#=A118-00-00,A118-00-00_0005      , 3
Up Type= 0
Dn Type= 3
Dn Slope=.007
Boundary for River Rch & Prof#=A118-00-00,A118-00-00_0005      , 4
Up Type= 0
Dn Type= 3
Dn Slope=.007
DSS Import GetInterval= 0
DSS Import GetPeak= 0
DSS Import FillOption= 0

--- A118_00_00.f02 (steady flow) ---

Flow Title=Floodway
Version=Version 3.0.1  Mar 2001
Number of Profiles= 2
Profile Names=1PCT_100yr, 1PCTFloodway_100yrFW
River Rch & RM=A118-00-00,A118-00-00_0005      ,1445.23
    1393    1393
River Rch & RM=A118-00-00,A118-00-00_0005      ,1073.142
    1467    1467
Boundary for River Rch & Prof#=A118-00-00,A118-00-00_0005      , 1
Up Type= 0
Dn Type= 3
Dn Slope=.007
Boundary for River Rch & Prof#=A118-00-00,A118-00-00_0005      , 2
Up Type= 0
Dn Type= 3
Dn Slope=.007
DSS Import GetInterval= 0
DSS Import GetPeak= 0
DSS Import FillOption= 0

--- A118_00_00.g01 (geometry) ---

Geom Title=A118-00-00 June 2007
Version=Version 3.0.1  Mar 2001

River Reach=A118-00-00     ,A118-00-00_0005
Reach XY= 30
       3184769.5       13766314.       3184280.5    13765787.999
      3184086.25    13765748.999      3183994.75       13765646.
      3183888.75    13765587.999      3183572.75       13765663.
      3183350.25    13765428.999      3182967.75    13765329.001
       3182763.5    13765177.001       3182531.5       13765110.
        3182415.       13765024.        3182353.       13764918.
      3182345.75       13764858.      3182365.25       13764375.
      3182353.25       13764326.      3182240.75       13764186.
       3181977.5       13763931.       3181947.5       13763866.
        3181946.       13763771.        3181910.       13763659.
        3181833.       13763159.       3181783.5       13762992.
       3181634.5       13762800.      3181491.75       13762658.
        3181397.       13762598.        3181263.       13762440.
       3181133.5       13762339.        3180886.    13762185.001
      3180415.75       13762024.        3180243.    13761915.999

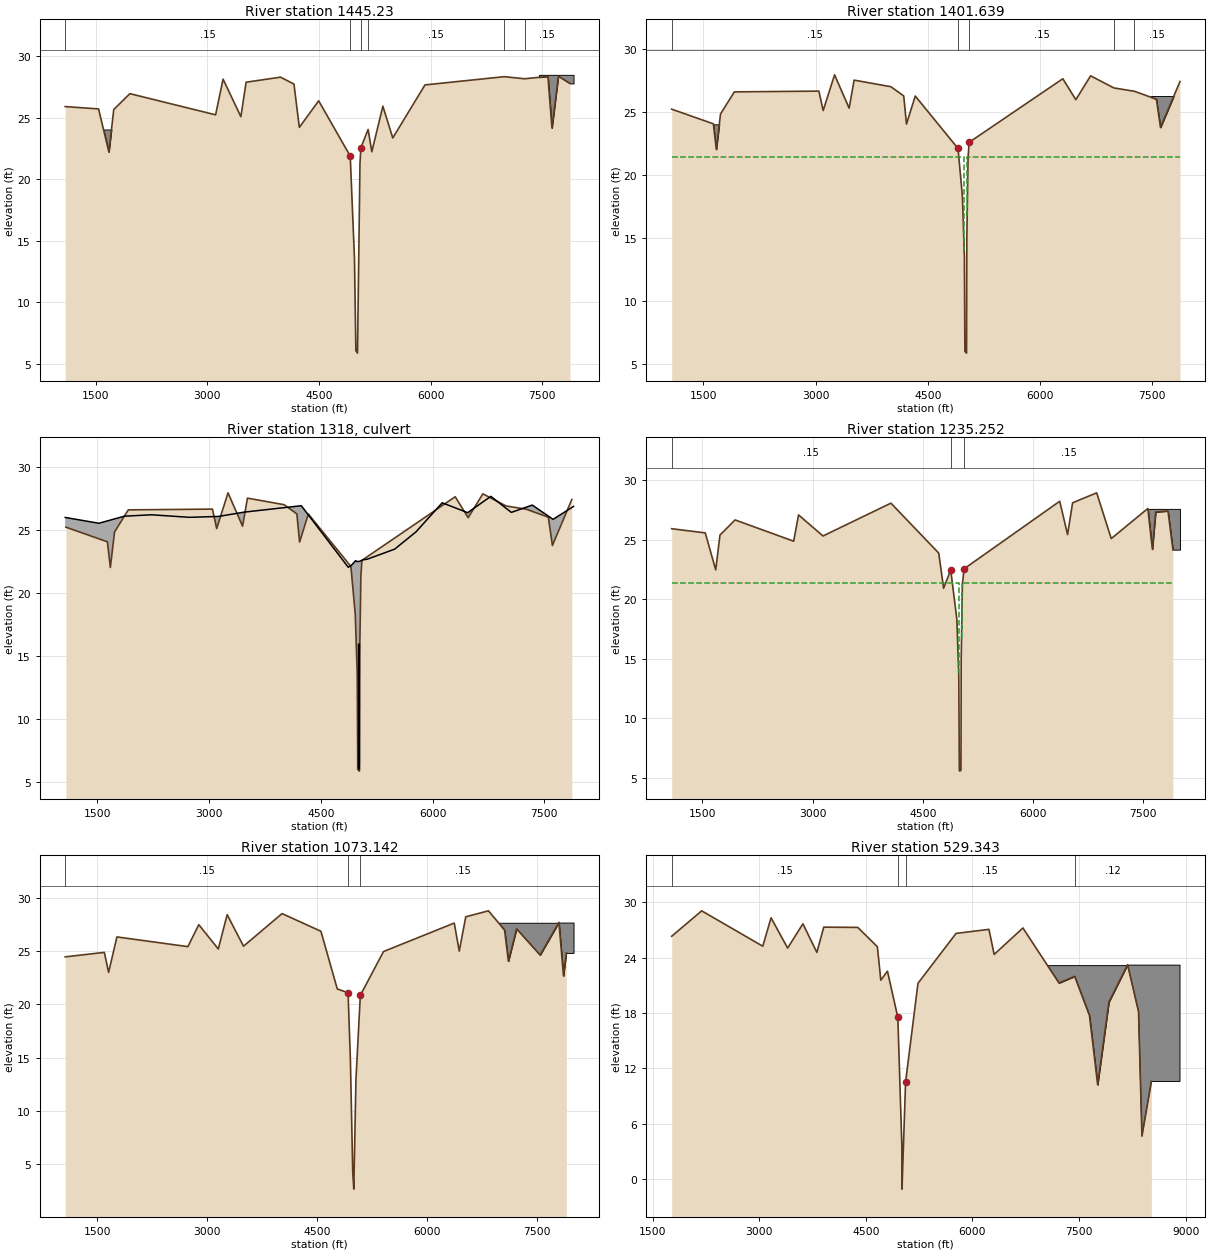
Type RM Length L Ch R = 1 ,1445.23 ,40,43.59,40.15
XS GIS Cut Line= 6
     3184337.879    13759988.183     3182807.502    13761356.475
     3181483.973    13762623.556     3180302.256     13763635.36
     3180021.266    13763953.316     3179518.213    13764716.955
#Sta/Elev= 30
 1089.35   25.91 1537.61   25.72 1676.55   22.22 1741.65   25.67  1958.8   26.96
 3110.67   25.24  3211.2   28.14 3450.24   25.09  3520.7   27.89 3982.55    28.3
 4163.86   27.74 4235.64   24.22 4495.81   26.38    4920   21.89    4977   13.57
  4995.8    6.08 5017.55    5.88    5051   21.29    5063   22.57 5160.17   24.05
 5210.15   22.24 5358.66   25.94 5491.57   23.36 5924.55   27.67 6990.94   28.34
 7262.28   28.17 7576.53   28.36 7631.37   24.16 7717.52   28.38 7872.79   27.79
#Mann= 6 ,-1 , 0
 1089.35     .15       0    4920    .035       0    5063     .07       0
 5160.17     .15       0 6990.94     .07       0 7262.28     .15       0
#Block Obstruct= 2 ,-1
 7457.11 7920.99   28.49    1500    2000   24.05
Bank Sta=4920,5063
XS Rating Curve= 0
Exp/Cntr=.5,.3

Type RM Length L Ch R = 1 ,1401.639,165,166.39,165.6
XS GIS Cut Line= 6
     3184311.046    13759958.519     3182779.608     13761327.76
     3181457.421    13762593.611      3180274.99    13763606.057
     3179988.317     13763930.45     3179486.639    13764692.397
#Sta/Elev= 30
 1078.53    25.2 1635.26   24.04 1675.27   22.01 1731.18   24.82 1915.85   26.57
 3045.14   26.63 3102.41   25.09  3254.7   27.92 3449.26   25.28 3515.69    27.5
 4006.56   26.98 4178.39   26.25 4215.18   24.02 4332.44   26.24 4903.66   22.09
 4962.35   18.31 4988.44   13.57 4995.73    6.02 5017.55    5.88 5021.37   14.95
 5037.65   21.29 5051.41   22.57 6303.61   27.61 6477.52   25.95 6674.91   27.84
  6986.2   26.88 7257.81   26.62 7553.61   25.99  7608.6   23.75 7868.95   27.39
#Mann= 5 ,-1 , 0
 1078.53     .15       0 4903.66    .035       0 5051.41     .15       0
  6986.2     .07       0 7257.81     .15       0
#XS Ineff= 2 , 0
       0    4987    21.4    5026       0    21.4
Permanent Ineff=
       F       F
#Block Obstruct= 2 ,-1
 7476.59 7943.46   26.24    1500    1770      24
Bank Sta=4903.66,5051.41
XS Rating Curve= 0
Exp/Cntr=.5,.3

Type RM Length L Ch R = 2 ,1318    ,,,
BEGIN DESCRIPTION:
BLACKHAWK DR
END DESCRIPTION:
Bridge Culvert--1,0,-1,-1, 0
Deck Dist Width WeirC Skew NumUp NumDn MinLoCord MaxHiCord MaxSubmerge Is_Ogee
35,95,2.6,0, 24, 24, , , .95, 0, 0,0,,
    1069    1521    1862    2228    2738    3127    3469    4238 4868.63 4918.31
    4967  4982.1 5019.14 5071.23 5121.27    5491    5776    6129    6471    6782
    7057    7338    7617    7892
   25.97   25.51   26.07   26.18   25.98   26.05   26.39    26.9   22.02   22.23
   22.55   22.48   22.49   22.62   22.66   23.46   24.82   27.13   26.35   27.64
   26.37   26.95   25.82   26.84
                                                                                
                                                                                
                                
    1069    1521    1862    2228    2738    3127    3469    4238 4868.63 4918.31
    4967  4982.1 5019.14 5071.23 5121.27    5491    5776    6129    6471    6782
    7057    7338    7617    7892
   25.97   25.51   26.07   26.18   25.98   26.05   26.39    26.9   22.02   22.23
   22.55   22.48   22.49   22.62   22.66   23.46   24.82   27.13   26.35   27.64
   26.37   26.95   25.82   26.84
                                                                                
                                                                                
                                
BR Coef=-1 , 0 , 0 ,, 0 ,,,.8,0,,0,
WSPro=,,,, 1 ,,,, 0 ,,,, 0 ,,,,-1 ,-1 ,-1 , 0 , 0 , 0 , 0 , 0
Multiple Barrel Culv=2,10,8,165,.012,.7,1,8,3,6.055,5.653, 2,Culvert #1  , 0 ,1
    5001    5001    5012    5012
Culvert Bottom n=.012
BC Design=,, 0 ,, 0 ,,,,,,

Type RM Length L Ch R = 1 ,1235.252,160,162.11,160.59
XS GIS Cut Line= 6
     3184200.358    13759836.153     3182664.543    13761209.311
     3181347.894    13762470.087     3180162.519    13763485.183
     3179852.403    13763836.127     3179356.396    13764591.097
#Sta/Elev= 30
 1082.36   25.94  1539.2   25.59 1681.63   22.48 1739.54   25.41 1945.05   26.68
 2742.16   24.89 2808.67    27.1 3141.32   25.33 4065.03   28.09 4715.86   23.89
 4781.89   20.93 4878.78   22.47 4962.35   18.31 4988.44   13.57 4995.93    5.63
 5000.85    5.55 5018.24    5.62 5021.37   14.95 5037.65   21.29    5061   22.57
  6361.8   28.25 6468.49   25.45 6536.94   28.12 6864.36   28.96 7062.82   25.11
  7560.4   27.64 7622.47   24.21 7667.55   27.35 7834.67   27.43 7901.58   24.18
#Mann= 3 ,-1 , 0
 1082.36     .15       0 4878.78     .04       0    5061     .15       0
#XS Ineff= 2 , 0
       0    4987    21.4    5026       0    21.4
Permanent Ineff=
       F       F
#Block Obstruct= 1 ,-1
 7557.73 7998.06   27.61
Bank Sta=4878.78,5061
XS Rating Curve= 0
Exp/Cntr=.5,.3

Type RM Length L Ch R = 1 ,1073.142,631.84,543.8,465.85
XS GIS Cut Line= 6
     3184093.025    13759717.496     3182552.966    13761094.451
     3181241.686    13762350.307     3180053.456    13763367.972
     3179720.608    13763744.661       3179230.1    13764492.866
#Sta/Elev= 30
 1059.47   24.47 1594.12   24.89 1652.64   23.01 1766.13   26.34 2736.11   25.43
 2884.86   27.49 3151.17   25.21 3272.82   28.43 3496.02   25.47 4022.67   28.53
 4554.03   26.87 4777.15   21.46 4924.74    21.1 4956.63    14.8 4988.58    4.25
 5003.15    2.67 5032.37   12.94 5092.37   20.86 5409.35   24.97 6375.97   27.64
 6444.21   25.01 6533.16   28.23 6843.32   28.79 7063.29   26.99 7115.74   24.06
  7227.5    27.1 7548.88   24.64 7806.12   27.71 7868.64   22.68 7906.61   24.84
#Mann= 3 ,-1 , 0
 1059.47     .15       0 4924.74    .035       0 5092.37     .15       0
#Block Obstruct= 2 ,-1
 6892.19 7805.82   27.67 7805.26 8005.74   27.69
Bank Sta=4924.74,5092.37
XS Rating Curve= 0
Exp/Cntr=.3,.1

Type RM Length L Ch R = 1 ,529.343 ,406.92,529.34,311.08
XS GIS Cut Line= 6
     3182075.451    13759180.333     3181023.858    13761483.803
     3180572.689       13762404.     3180342.428    13762731.214
     3180078.209    13763036.767     3178330.666    13764670.262
#Sta/Elev= 30
 1764.93   26.32 2187.64   29.08 3047.33   25.24 3164.11   28.32 3397.57   25.04
 3612.58   27.67 3808.77   24.57 3905.88   27.31  4384.7   27.28  4660.8   25.19
 4709.22   21.56  4803.1   22.53    4949   17.51 5005.26    3.62 5007.65   -1.11
    5058   10.51 5232.61   21.22 5768.76   26.63 6231.27   27.07 6305.13   24.35
 6709.89   27.22 7218.09   21.25 7438.12   21.97 7646.84   17.72 7762.05   10.21
 7921.01   19.19 8183.55   23.24 8337.79   18.14 8385.63    4.65 8518.73   10.57
#Mann= 4 ,-1 , 0
 1764.93     .15       0    4949    .035       0    5058     .15       0
 7438.12     .12       0
#Block Obstruct= 2 ,-1
 6858.24 8173.98   23.19 8177.17 8921.26   23.19
Bank Sta=4949,5058
XS Rating Curve= 0
Exp/Cntr=.3,.1

Chan Stop Cuts=-1